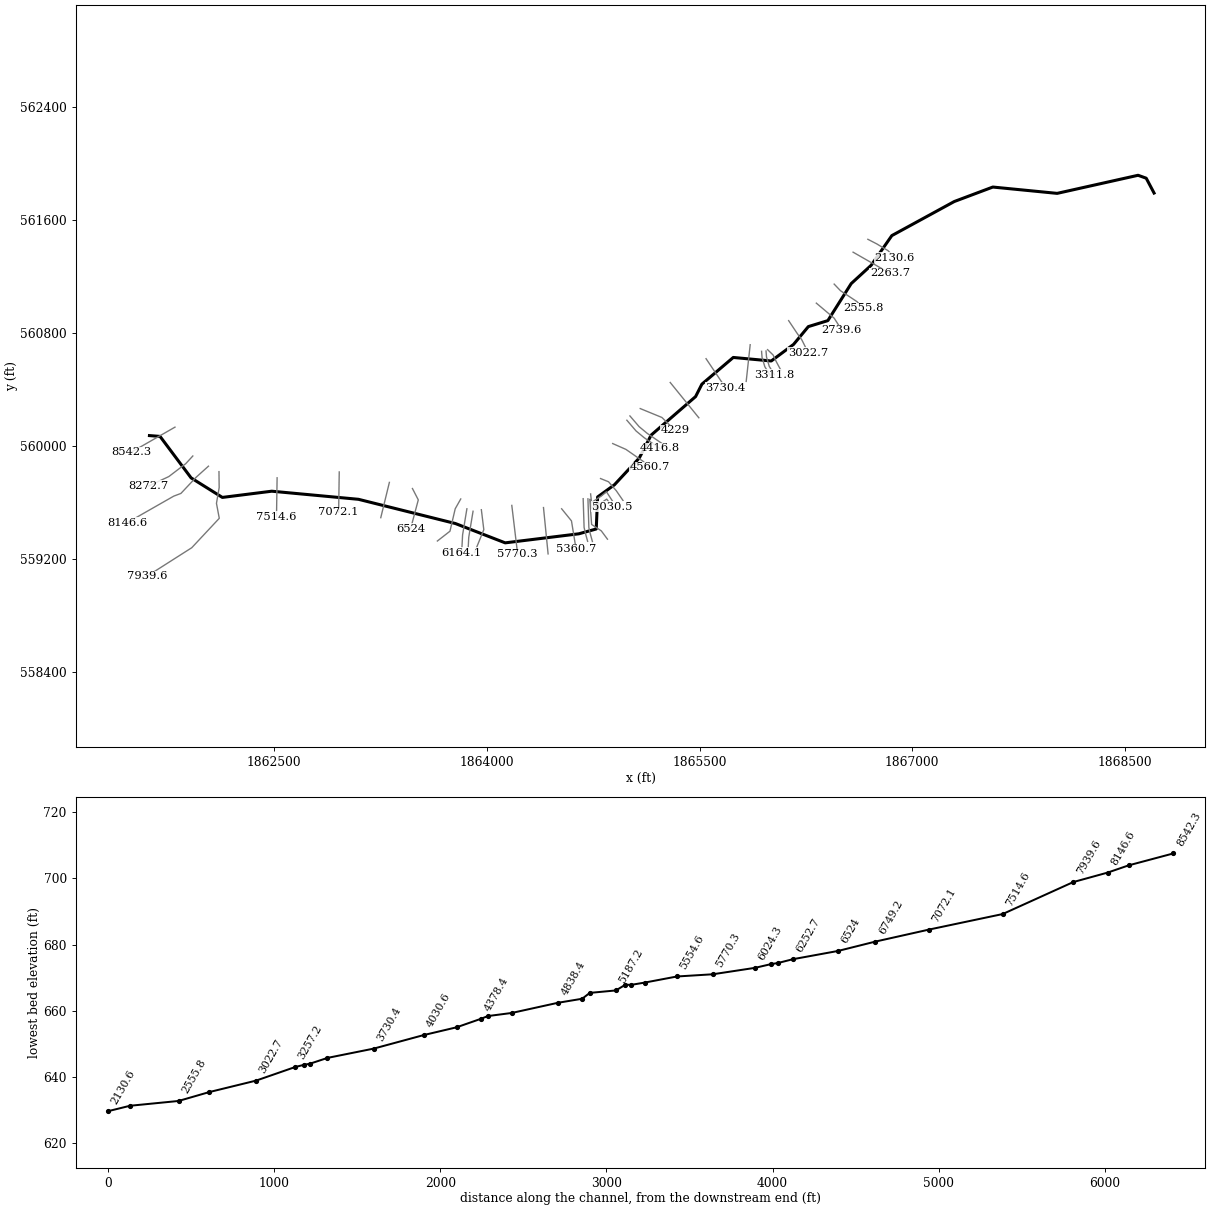
--- GABESCR.prj (project) ---

Proj Title=GABESCR
Current Plan=p01
Default Exp/Contr=0,0
English Units
Geom File=g01
Flow File=f01
Plan File=p01
BEGIN DESCRIPTION:
END DESCRIPTION:
DSS Export Rating Curves= 0
DSS Export Rating Curve Sorted= 0
DSS Export Volume Flow Curves= 0
DXF OffsetX= 0
DXF OffsetY= 0
DXF ScaleX= 0
DXF ScaleY= 0

--- GABESCR.p01 (plan) ---

Plan Title=Floodplain
Program Version=4.00
Geom File=g01
Flow File=f01
K Sum by GR=0
Std Step Tol=0.01
Critical Tol=0.01
Num of Std Step Trials=20
Max Error Tol=0.3
Flow Tol Ratio=0.001
Split Flow NTrial=30
Split Flow Tol=0.02
Split Flow Ratio=0.02
Log Output Level=0
Friction Slope Method=1
Unsteady Friction Slope Method=2
Unsteady Bridges Friction Slope Method=1
Global Log Level=0
CheckData=False
Run HTab=0
Run UNet=0
Run PostProcess=0
UNET Theta=0
UNET Theta Warmup=0
UNET ZTol=0
UNET ZSATol=0
UNET MxIter=0
UNET MaxInSteps=0
UNET DtIC=0
UNET DtMin=0
UNET MaxCRTS=0
UNET WFStab=0
UNET SFStab=0
UNET WFX=0
UNET SFX=0
UNET DSS MLevel=0
UNET DZMax Abort=0
UNET Convert EG Bridges=0
UNET Use Existing IB Tables=0
UNET Froude Limit=0
UNET Froude Power=0
Write IC File=0
Echo Input=False
Echo Output=False
Write Detailed=0

--- GABESCR.f01 (steady flow) ---

Flow Title=NFF Regression Equation
Program Version=4.10
Number of Profiles= 1
Profile Names=P100yr
River Rch & RM=GABESCR,Main            ,8542.3
949.8577
River Rch & RM=GABESCR,Main            ,5770.3
1006.979
River Rch & RM=GABESCR,Main            ,3022.7
1119.682
Boundary for River Rch & Prof#=GABESCR,Main            , 1
Up Type= 0
Dn Type= 1
Dn Known WS=634.01
DSS Import GetInterval= 0
DSS Import GetPeak= 0
DSS Import FillOption= 0

--- GABESCR.g01 (geometry) ---

Geom Title=USGS 10m DEM
Program Version=4.10

River Reach=GABESCR         ,Main
Reach XY= 30
     1861619.175      560074.183     1861694.004      560068.388
     1861913.012      559775.138     1862133.489      559637.001
     1862482.023      559680.954     1863094.002      559623.662
     1863777.369      559452.539     1864128.932       559315.82
      1864648.68      559379.839      1864771.32      559413.901
     1864781.058      559640.256     1864899.331      559725.977
     1865075.112      559915.864     1865158.663      560077.539
     1865472.248      560349.892     1865516.735      560437.782
      1865738.09      560626.584     1866006.102      560601.628
     1866163.437      560718.815     1866267.604      560844.683
     1866405.407      560887.001     1866569.957      561148.662
     1866711.397      561278.711     1866856.796      561488.129
     1867297.335      561729.015     1867569.369      561831.381
     1868023.082      561786.683     1868593.992      561914.562
     1868651.501      561893.945     1868706.933      561788.956

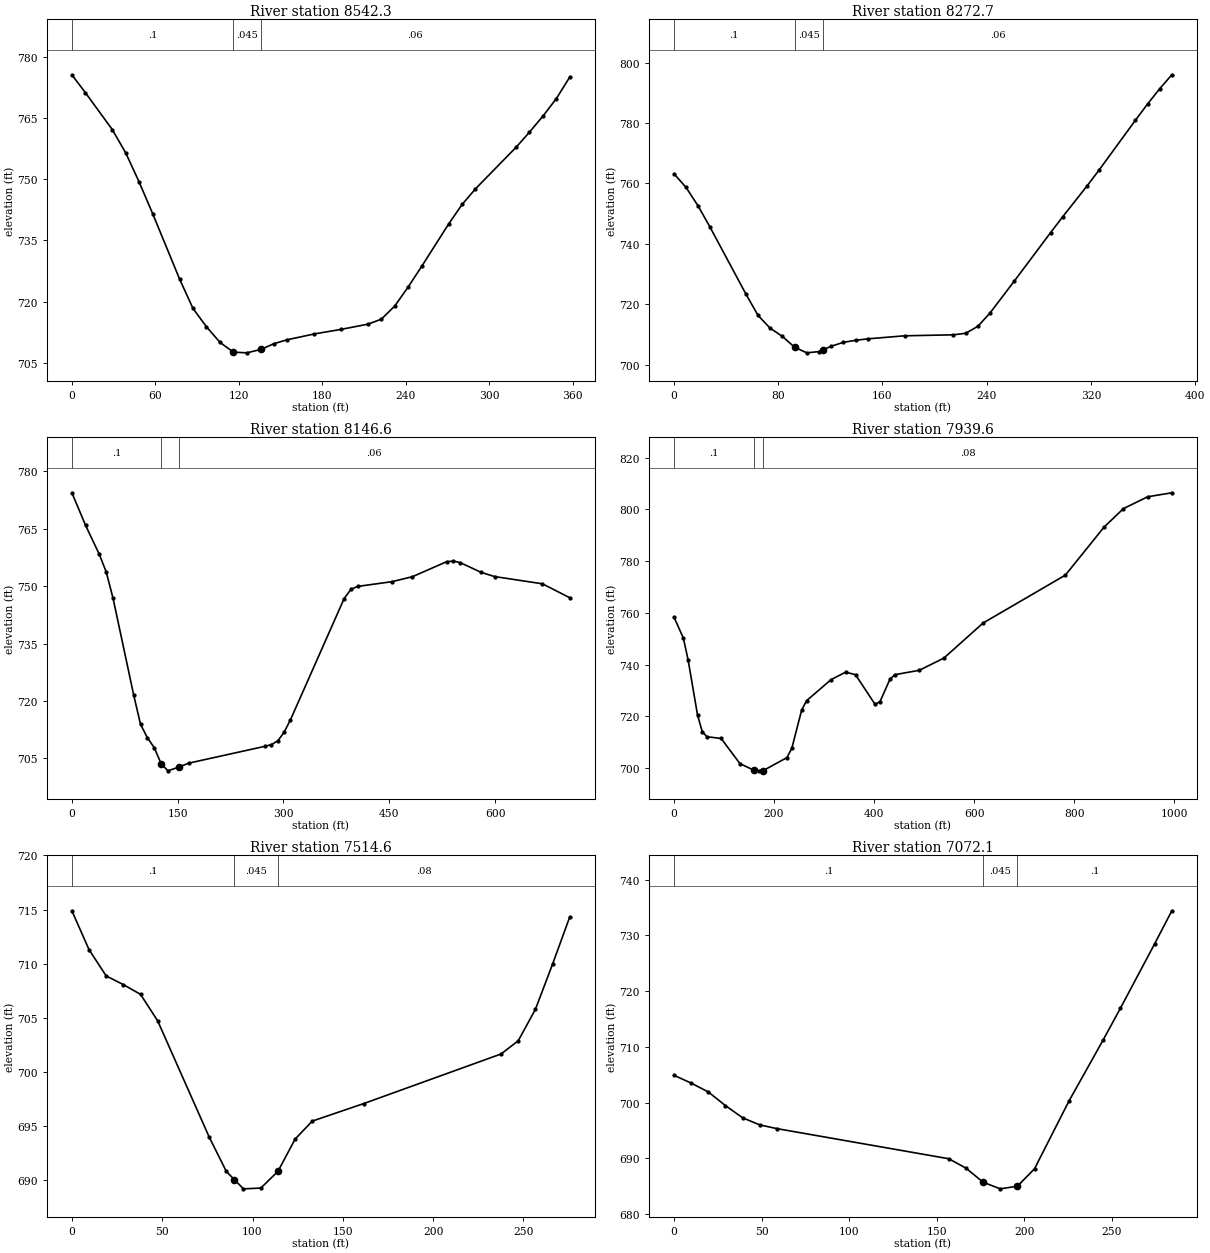
Type RM Length L Ch R = 1 ,8542.3  ,264.8,269.7,277.6
XS GIS Cut Line= 2
      1861799.34       560133.92     1861489.011      559955.968
#Sta/Elev= 30
       0  775.54     9.7  771.17      29  762.15    38.7  756.42    48.3  749.33
      58   741.6    77.4  725.56      87  718.38    96.7  713.89   106.4  710.08
     116  707.68   125.7  707.51   135.9  708.35     145  709.73   154.7  710.71
     174  712.12   193.4  713.25   212.7  714.52   222.4  715.75     232  718.97
   241.7  723.66   251.4   728.7   270.7  739.03   280.4  743.82     290  747.64
   319.1  757.78   328.7  761.47   338.4   765.4   348.1  769.72   357.7  774.96
#Mann= 3 , 0 , 0
       0      .1       0     116    .045       0   135.9     .06       0
Bank Sta=116,135.9
XS Rating Curve= 0 ,0
Exp/Cntr=0.3,0.1

Type RM Length L Ch R = 1 ,8272.7  ,122.1,126.1,129.5
XS GIS Cut Line= 4
     1861925.208      559929.927     1861875.295      559875.673
     1861755.938      559784.527     1861612.708      559717.253
#Sta/Elev= 30
       0   763.2     9.2  758.69    18.4  752.61    27.6  745.56    55.3  723.28
    64.5   716.3    73.7  712.09    83.1  709.37    92.5  705.78   101.9   703.9
   111.3  704.32   114.5  704.92   120.6  706.07     130  707.38   139.4  708.05
   148.8  708.54     177  709.54   214.5  709.87   223.9  710.38   233.2  712.68
   242.5  717.07   261.1  727.61   289.1  743.74   298.4  748.99     317  759.15
   326.3  764.44   354.2  780.94   363.5   786.3   372.8  791.35   382.1  795.96
#Mann= 3 , 0 , 0
       0      .1       0    92.5    .045       0   114.5     .06       0
Bank Sta=92.5,114.5
XS Rating Curve= 0 ,0
Exp/Cntr=0.3,0.1

Type RM Length L Ch R = 1 ,8146.6  ,193,207,220.2
XS GIS Cut Line= 5
     1862035.531      559857.943     1861948.726      559779.818
     1861841.087      559665.235     1861790.739      559646.138
     1861462.614      559458.638
#Sta/Elev= 30
       0  774.41    19.5  765.88    38.9   758.3    48.7  753.71    58.4  746.81
    87.6  721.58    97.3   713.9     107  710.39   116.8  707.76   126.6  703.55
   136.3  701.72   151.3  702.69   165.9  703.74     274  708.14     283  708.59
     292  709.57   300.9  711.81   309.9  715.06     386  746.76   395.7  749.16
   405.4  749.94   453.8  751.17   482.9  752.48   531.3  756.39     541  756.55
   550.7  756.15   579.8  753.64   599.2  752.51     667  750.62   705.8  746.98
#Mann= 3 , 0 , 0
       0      .1       0   126.6    .045       0   151.3     .06       0
Bank Sta=126.6,151.3
XS Rating Curve= 0 ,0
Exp/Cntr=0.3,0.1

Type RM Length L Ch R = 1 ,7939.6  ,422,425,428.3
XS GIS Cut Line= 6
      1862109.67      559819.249     1862111.052      559706.207
     1862091.955      559595.096      1862111.84      559489.388
     1861917.682      559281.361     1861599.767      559078.429
#Sta/Elev= 30
       0  758.33    18.8  750.17    28.3  741.67    47.1   720.4    56.5     714
      66  712.05    94.2  711.39   131.8  701.66     160  699.07   169.4  698.86
   178.5  698.98   225.8  703.98   235.6  707.65   255.1  722.31   264.9  725.99
   313.8  734.13   343.2  737.05   362.8  736.05     402  724.56   411.8  725.65
   431.5  734.24   441.3  736.05   490.4  737.77   539.4  742.48   617.9  756.06
   782.3  774.59   859.7  793.17   898.4  800.32   946.7  804.89   995.1  806.44
#Mann= 3 , 0 , 0
       0      .1       0     160    .045       0   178.5     .08       0
Bank Sta=160,178.5
XS Rating Curve= 0 ,0
Exp/Cntr=0.3,0.1

Type RM Length L Ch R = 1 ,7514.6  ,442.4,442.5,442.5
XS GIS Cut Line= 2
     1862519.826      559775.847     1862515.486      559500.239
#Sta/Elev= 20
       0  714.89     9.5   711.3      19  708.87    28.5  708.07      38  707.17
    47.5  704.72      76  693.99    85.5  690.81    89.9  690.06      95   689.2
   104.6  689.27   114.1  690.82   123.6   693.8   133.1  695.46   161.6  697.08
   237.6  701.66   247.1  702.88   256.6  705.78   266.1  709.96   275.6  714.31
#Mann= 3 , 0 , 0
       0      .1       0    89.9    .045       0   114.1     .08       0
Bank Sta=89.9,114.1
XS Rating Curve= 0 ,0
Exp/Cntr=0.3,0.1

Type RM Length L Ch R = 1 ,7072.1  ,327.9,322.9,317.8
XS GIS Cut Line= 2
     1862958.195      559817.079     1862953.854      559532.791
#Sta/Elev= 18
       0  704.89     9.8  703.49    19.6   701.9    29.4  699.45    39.2  697.26
      49  695.99    58.8  695.32   156.9  689.92   166.7  688.24   176.5  685.71
   186.3  684.52   196.1  684.99   205.9  688.13   225.5  700.24   245.1  711.24
   254.9   716.9   274.5  728.49   284.3   734.4
#Mann= 3 , 0 , 0
       0      .1       0   176.5    .045       0   196.1      .1       0
Bank Sta=176.5,196.1
XS Rating Curve= 0 ,0
Exp/Cntr=0.3,0.1

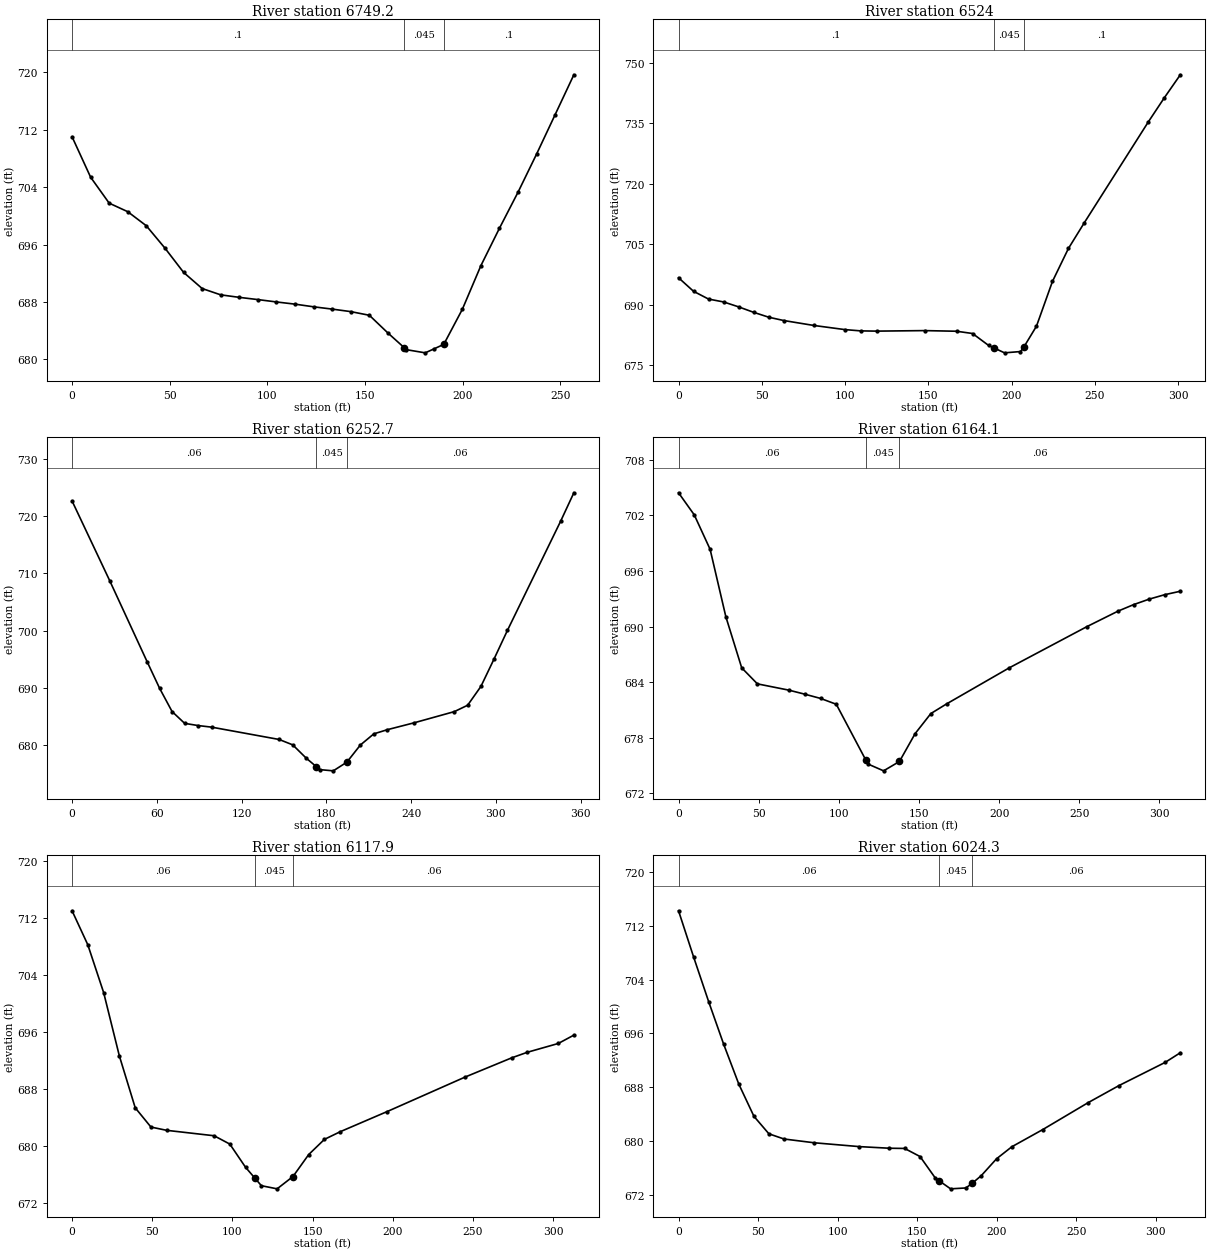
Type RM Length L Ch R = 1 ,6749.2  ,225.7,225.2,224.8
XS GIS Cut Line= 2
     1863311.927      559743.295     1863251.163      559493.729
#Sta/Elev= 30
       0  711.03     9.5  705.39      19  701.77    28.5  700.58      38  698.62
    47.6  695.48    57.1  692.11    66.6  689.86    76.1  688.98    85.6  688.63
    95.1  688.32   104.6  687.99   114.2  687.68   123.7  687.31   133.2  686.99
   142.7  686.64   152.2  686.13   161.7  683.66   170.1   681.6   171.2  681.33
   180.8  680.89   185.1  681.42   190.3  682.07   199.8  686.96   209.3  693.05
   218.8  698.27   228.3  703.29   237.8  708.61   247.3  714.11   256.9  719.68
#Mann= 3 , 0 , 0
       0      .1       0   170.1    .045       0   190.3      .1       0
Bank Sta=170.1,190.3
XS Rating Curve= 0 ,0
Exp/Cntr=0.3,0.1

Type RM Length L Ch R = 1 ,6524    ,270.6,271.3,272
XS GIS Cut Line= 3
     1863474.688      559699.892      1863515.92      559619.597
     1863461.667      559415.604
#Sta/Elev= 27
       0   696.7       9  693.34      18  691.41    27.1  690.69    36.1  689.47
    45.1  688.12    54.2   686.9    63.2  686.08    81.2  684.86    99.9  683.83
   109.4  683.51     119  683.45   147.8  683.58     167  683.42   176.6  682.86
   186.2  679.91   189.3  679.31   195.8  678.06   205.4  678.38   207.4  679.49
     215  684.68   224.6  695.79   234.2  703.98   243.8   710.4   282.2   735.4
   291.8  741.38   301.4  747.08
#Mann= 3 , 0 , 0
       0      .1       0   189.3    .045       0   207.4      .1       0
Bank Sta=189.3,207.4
XS Rating Curve= 0 ,0
Exp/Cntr=0.3,0.1

Type RM Length L Ch R = 1 ,6252.7  ,87.2,88.6,90.2
XS GIS Cut Line= 4
     1863815.399      559626.107     1863776.337      559556.663
     1863739.445      559398.243     1863650.469      559328.798
#Sta/Elev= 26
       0  722.64    26.6  708.76    53.1  694.62      62  689.95    70.8  685.91
    79.7  683.85    89.2  683.47    98.8  683.19   146.6  681.04   156.2   680.1
   165.8  677.77     173  676.28   175.4  675.78   184.9  675.57   194.5  677.08
   204.1  680.08   213.6  682.02   223.2  682.75   242.3  683.96   270.6   685.9
     280  687.01   289.4  690.29   298.8  695.13   308.2  700.08   345.8  719.09
   355.2  724.07
#Mann= 3 , 0 , 0
       0     .06       0     173    .045       0   194.5     .06       0
Bank Sta=173,194.5
XS Rating Curve= 0 ,0
Exp/Cntr=0.3,0.1

Type RM Length L Ch R = 1 ,6164.1  ,46.1,46.2,46.1
XS GIS Cut Line= 3
     1863858.802      559556.663      1863828.42      559372.201
      1863821.91      559246.333
#Sta/Elev= 24
       0  704.43     9.8  702.05    19.7  698.33    29.5  691.07    39.4  685.55
    49.2  683.82    68.9  683.14    78.7  682.71    88.6  682.25    98.4  681.62
   116.7  675.64   118.1  675.18   127.9  674.44   137.8  675.45   147.6  678.46
   157.4  680.62   167.3  681.67   206.3  685.55   254.8     690   274.2  691.67
   283.9  692.37   293.6  692.96   303.3  693.44     313  693.81
#Mann= 3 , 0 , 0
       0     .06       0   116.7    .045       0   137.8     .06       0
Bank Sta=116.7,137.8
XS Rating Curve= 0 ,0
Exp/Cntr=0.3,0.1

Type RM Length L Ch R = 1 ,6117.9  ,98.4,93.5,88.5
XS GIS Cut Line= 3
     1863902.205      559539.302     1863871.823       559354.84
     1863865.313      559228.972
#Sta/Elev= 23
       0  713.07     9.8  708.31    19.7  701.59    29.5   692.7    39.4  685.42
    49.2  682.72      59  682.26    88.6   681.5    98.4  680.33   108.2  677.08
   113.8  675.61   118.1  674.49   127.9  674.05   137.8  675.78   147.6  678.86
   157.4  680.99   167.3  682.07   196.6   684.9   245.1  689.73   274.2  692.43
   283.9  693.21   303.3  694.45     313  695.62
#Mann= 3 , 0 , 0
       0     .06       0   113.8    .045       0   137.8     .06       0
Bank Sta=113.8,137.8
XS Rating Curve= 0 ,0
Exp/Cntr=0.3,0.1

Type RM Length L Ch R = 1 ,6024.3  ,242.8,254,265.2
XS GIS Cut Line= 3
     1863960.799      559550.152      1863978.16      559409.093
     1863913.056      559248.503
#Sta/Elev= 26
       0  714.19     9.5  707.32      19  700.67    28.4  694.38    37.9  688.48
    47.4  683.71    56.8  681.12    66.3  680.35    85.3  679.79   113.7  679.22
   132.6  678.98   142.1  678.95   151.8  677.75   161.4  674.56   163.9  674.14
     171  672.96   180.6  673.09  184.46  673.76   190.3  674.92   199.9  677.42
   209.5   679.2   228.8  681.73   257.6  685.76   276.9  688.28   305.8   691.7
   315.4  693.14
#Mann= 3 , 0 , 0
       0     .06       0   163.9    .045       0  184.46     .06       0
Bank Sta=163.9,184.46
XS Rating Curve= 0 ,0
Exp/Cntr=0.3,0.1

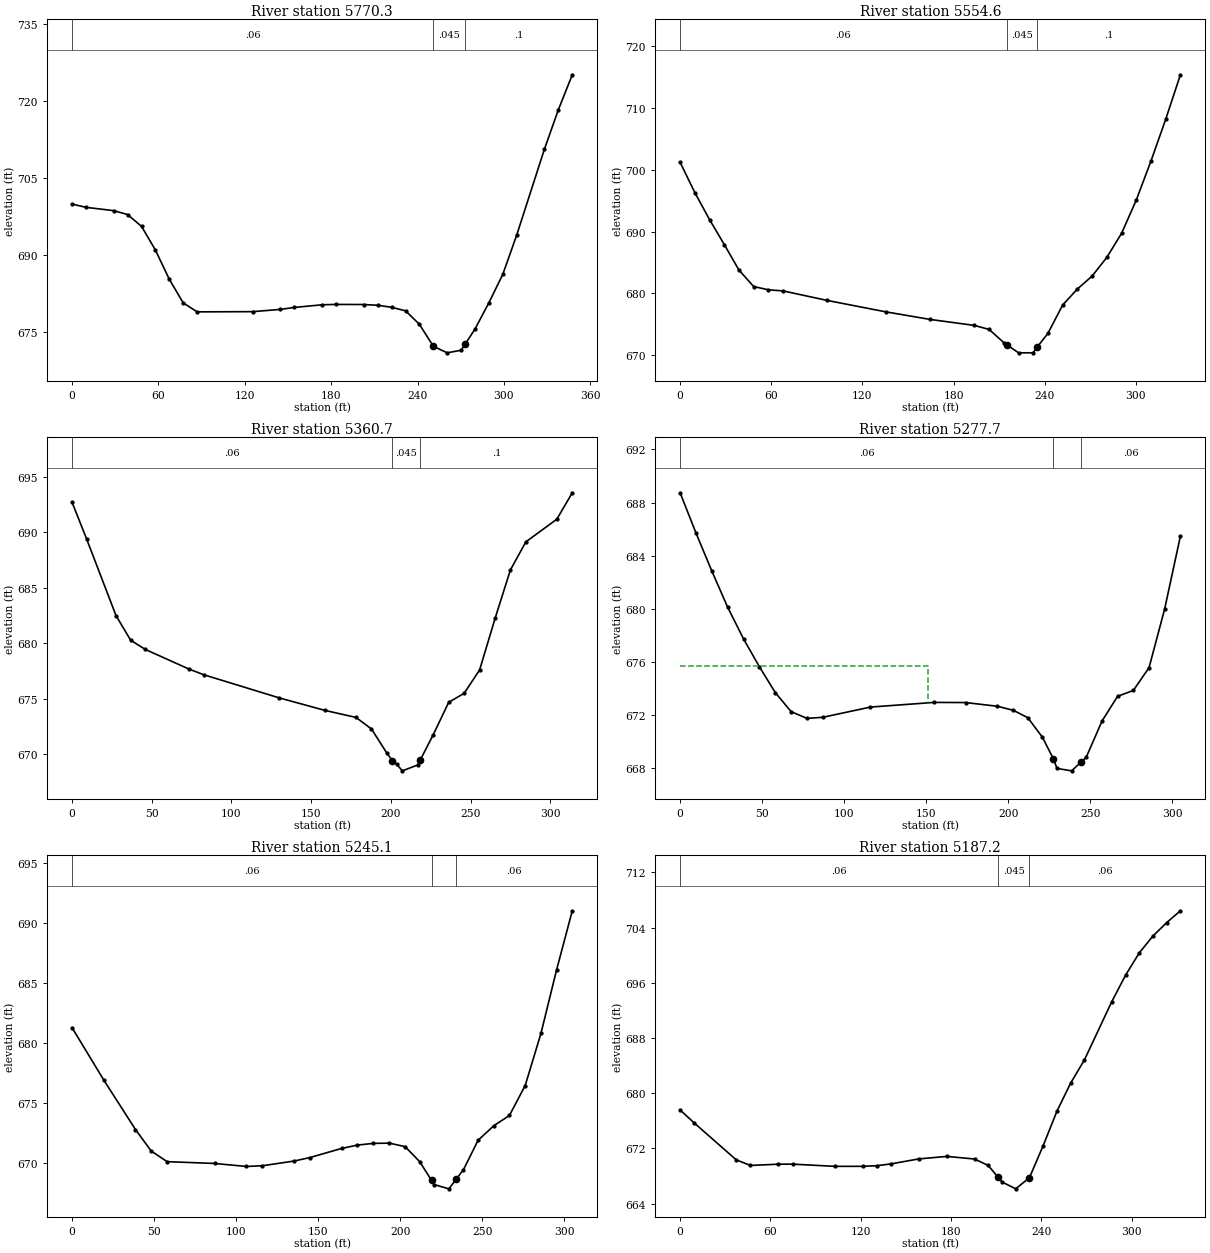
Type RM Length L Ch R = 1 ,5770.3  ,216.1,215.7,215.2
XS GIS Cut Line= 2
     1864175.642      559580.534     1864216.875      559235.482
#Sta/Elev= 30
       0     700     9.6  699.36      29  698.71    38.6  697.95    48.3  695.65
    57.9  691.06    67.6  685.34    77.2  680.77    86.9     679   125.5  679.04
   144.8  679.48   154.4  679.86   173.8  680.38   183.4  680.45   202.7  680.43
   212.4  680.28     222  679.89   231.7   679.2   241.3  676.58     251   672.3
   260.6  671.02   270.3  671.53   273.1  672.73   279.9  675.64   289.6  680.79
   299.2  686.28   308.9  693.95   328.2  710.73   337.8  718.34   347.5  725.17
#Mann= 3 , 0 , 0
       0     .06       0     251    .045       0   273.1      .1       0
Bank Sta=251,273.1
XS Rating Curve= 0 ,0
Exp/Cntr=0.3,0.1

Type RM Length L Ch R = 1 ,5554.6  ,192.5,193.9,195.3
XS GIS Cut Line= 2
     1864399.167      559565.343     1864431.719      559237.652
#Sta/Elev= 28
       0  701.22     9.7   696.3    19.4  691.92    29.1  687.88    38.7  683.77
    48.4  681.09    58.1  680.56    67.8  680.38    96.8  678.84   135.6  676.98
   164.6  675.76   193.7  674.79   203.4  674.14   213.1     672   214.9  671.69
   222.8  670.35   232.4  670.36  234.99  671.28   242.1   673.5   251.8   678.1
   261.5  680.69   271.2  682.79   280.9  685.82   290.6  689.72   300.2  695.06
   309.9   701.4   319.6  708.16   329.3  715.39
#Mann= 3 , 0 , 0
       0     .06       0   214.9    .045       0  234.99      .1       0
Bank Sta=214.9,234.99
XS Rating Curve= 0 ,0
Exp/Cntr=0.3,0.1

Type RM Length L Ch R = 1 ,5360.7  ,81.6,83,84.9
XS GIS Cut Line= 3
     1864527.205      559556.663     1864596.649      559470.942
     1864629.201      559270.204
#Sta/Elev= 26
       0  692.71     9.2  689.38    27.6  682.49    36.8  680.27      46  679.44
    73.6  677.66    82.7  677.16   129.7  675.09   158.7  673.95   178.1  673.32
   187.8  672.28   197.5  670.09  200.89  669.44   203.5  669.11   207.2  668.51
   216.8  669.04   218.5  669.52   226.5  671.76   236.2  674.68   245.9  675.49
   255.6   677.6   265.3  682.24   274.9   686.6   284.6  689.13     304  691.17
   313.7  693.55
#Mann= 3 , 0 , 0
       0     .06       0  200.89    .045       0   218.5      .1       0
Bank Sta=200.89,218.5
XS Rating Curve= 0 ,0
Exp/Cntr=0.3,0.1

Type RM Length L Ch R = 1 ,5277.7  ,32.6,32.6,32.2
XS GIS Cut Line= 4
     1864679.115      559628.277     1864685.625      559425.369
     1864695.391      559381.966     1864710.582      559326.628
#Sta/Elev= 28
       0  688.74     9.7   685.7    19.3  682.86      29  680.12    38.7  677.73
    48.3  675.65      58   673.7    67.7  672.26    77.3  671.76      87  671.84
     116  672.61   154.7  672.96     174  672.95   193.4  672.67     203  672.37
   211.9  671.81   220.8  670.34  227.55   668.7   229.7  667.99   238.6  667.81
   244.3  668.46   247.5  668.83   257.1  671.55   266.6  673.42   276.2  673.86
   285.8  675.58   295.3  679.99   304.9  685.48
#Mann= 3 , 0 , 0
       0     .06       0  227.55    .045       0   244.3     .06       0
#XS Ineff= 2 , 0
          150.97  675.68
Permanent Ineff=
       F       F
Bank Sta=227.55,244.3
XS Rating Curve= 0 ,0
Exp/Cntr=0.3,0.1

Type RM Length L Ch R = 1 ,5245.1  ,38.4,57.9,76.4
XS GIS Cut Line= 4
     1864712.752      559627.192     1864719.262      559424.284
     1864729.028      559380.881     1864744.219      559325.543
#Sta/Elev= 28
       0  681.29    19.3  676.94    38.7  672.81    48.3  671.02      58  670.14
      87  669.99   106.3  669.74     116   669.8   135.3  670.19     145  670.48
   164.3  671.24     174  671.52   183.7  671.66   193.4  671.68     203  671.39
   211.9  670.14   219.1  668.59   220.8  668.23   229.7  667.88   234.1  668.67
   238.6  669.48   247.5  671.92   257.1  673.13   266.6  673.98   276.2  676.47
   285.8   680.8   295.3  686.07   304.9     691
#Mann= 3 , 0 , 0
       0     .06       0   219.1    .045       0   234.1     .06       0
Bank Sta=219.1,234.1
XS Rating Curve= 0 ,0
Exp/Cntr=0.3,0.1

Type RM Length L Ch R = 1 ,5187.2  ,131.3,156.7,184.3
XS GIS Cut Line= 4
     1864725.773      559622.852     1864738.794      559445.986
     1864807.153      559400.413     1864850.556      559341.819
#Sta/Elev= 28
       0  677.57     9.3   675.7    37.3  670.34    46.7  669.53    65.3  669.71
    74.7  669.72   102.7   669.4   121.3   669.4   130.7  669.49     140  669.75
   158.7  670.48   177.3  670.84   195.6  670.46   204.7  669.53   211.1  667.86
   213.9  667.13     223  666.14   232.1  667.76   241.2  672.38   250.4  677.41
   259.5  681.47   268.6  684.81   286.8  693.26     296  697.11   305.1  700.34
   314.2  702.78   323.3  704.72   332.4  706.43
#Mann= 3 , 0 , 0
       0     .06       0   211.1    .045       0   232.1     .06       0
Bank Sta=211.1,232.1
XS Rating Curve= 0 ,0
Exp/Cntr=0.3,0.1

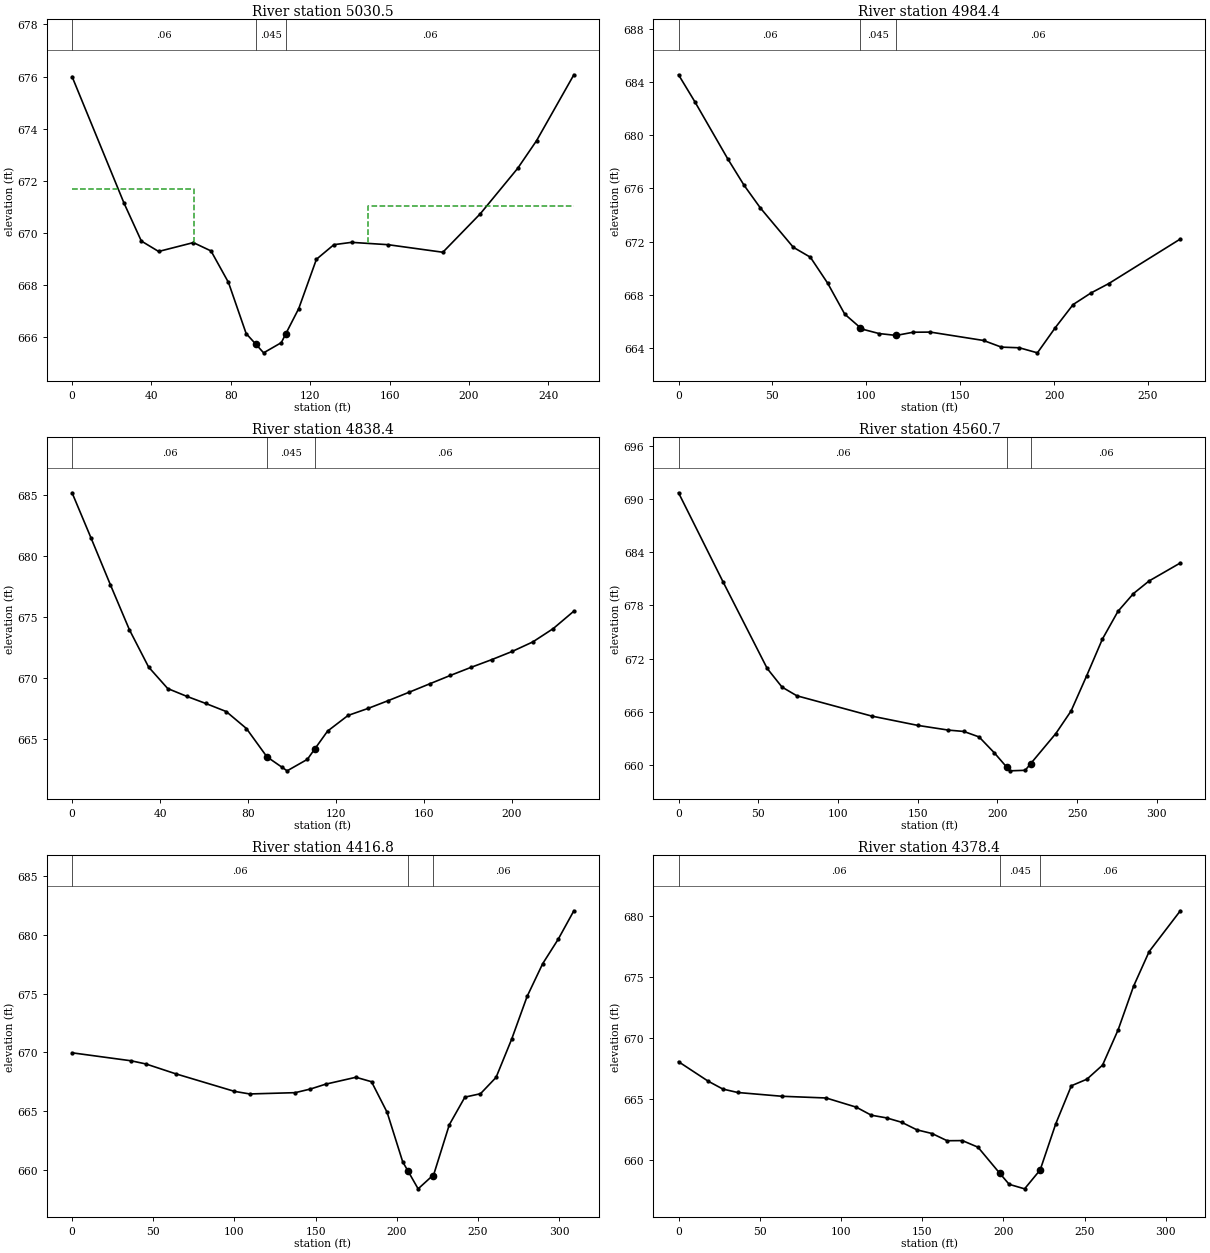
Type RM Length L Ch R = 1 ,5030.5  ,42.8,46.1,98.6
XS GIS Cut Line= 5
     1864731.198      559620.682     1864737.708      559559.918
     1864807.153       559598.98      1864845.13      559625.022
     1864884.193      559571.854
#Sta/Elev= 22
       0     676    26.2  671.14    34.9  669.69    43.6  669.29    61.1  669.63
      70  669.31    78.8   668.1    87.7  666.14    92.6  665.73    96.5   665.4
   105.4  665.79   107.6  666.12   114.2   667.1   123.1  668.99   131.9  669.55
   140.8  669.64   159.2  669.55   186.8  669.26   205.7  670.74   224.5  672.48
     234  673.54   252.8  676.07
#Mann= 3 , 0 , 0
       0     .06       0    92.6    .045       0   107.6     .06       0
#XS Ineff= 2 , 0
           61.38   671.7  149.34          671.02
Permanent Ineff=
       F       F
Bank Sta=92.6,107.6
XS Rating Curve= 0 ,0
Exp/Cntr=0.3,0.1

Type RM Length L Ch R = 1 ,4984.4  ,180.5,146,59.6
XS GIS Cut Line= 5
     1864731.675      559661.828     1864738.186      559601.064
     1864806.545      559646.637     1864843.438      559677.019
      1864884.67      559612.999
#Sta/Elev= 24
       0  684.54     8.7  682.51    26.2  678.22    34.9  676.23    43.6  674.52
    61.1  671.57    70.2  670.82    79.4  668.87    88.5  666.54    96.8  665.52
    97.6  665.42   106.8  665.08   115.9  664.94     125  665.18   134.1  665.19
   162.4  664.56   171.9  664.06   181.5  664.01   191.1  663.63   200.6  665.52
   210.1  667.26   219.6  668.13   229.1  668.84   267.2  672.19
#Mann= 3 , 0 , 0
       0     .06       0    96.8    .045       0   115.9     .06       0
Bank Sta=96.8,115.9
XS Rating Curve= 0 ,0
Exp/Cntr=0.3,0.1

Type RM Length L Ch R = 1 ,4838.4  ,272.1,277.7,283
XS GIS Cut Line= 4
     1864801.728      559770.421     1864858.151      559747.635
     1864912.405      559684.701     1864960.148      559615.256
#Sta/Elev= 28
       0  685.15     8.7  681.42    17.4  677.64    26.1  673.94    34.8   670.9
    43.5  669.14    52.2   668.5    60.8  667.92    70.1  667.26    79.3  665.87
    88.6  663.56    95.5   662.7    97.8  662.41     107  663.35   110.5  664.23
   116.2  665.66   125.5  666.94   134.7  667.52   143.9  668.16   153.3  668.84
   162.7  669.53     172  670.21   181.4  670.87   190.8   671.5   200.1  672.17
   209.5  672.95   218.8  674.04   228.2  675.47
#Mann= 3 , 0 , 0
       0     .06       0    88.6    .045       0   110.5     .06       0
Bank Sta=88.6,110.5
XS Rating Curve= 0 ,0
Exp/Cntr=0.3,0.1

Type RM Length L Ch R = 1 ,4560.7  ,144.1,144,144.3
XS GIS Cut Line= 4
     1864887.448      560017.817     1864980.764      559976.585
     1865099.037      559894.119      1865151.12      559849.631
#Sta/Elev= 23
       0  690.68    27.8  680.68    55.6  670.88    64.9  668.78    74.2   667.8
   121.2  665.51   150.1  664.46   169.3  663.93   178.9  663.78   188.5  663.16
   198.1  661.36   205.8  659.76   207.8  659.34   217.4   659.4   220.8  660.14
   236.6  663.54   246.2  666.09     256  670.07   265.8  674.18   275.6  677.32
   285.3  679.32   295.1  680.74   314.7  682.77
#Mann= 3 , 0 , 0
       0     .06       0   205.8    .045       0   220.8     .06       0
Bank Sta=205.8,220.8
XS Rating Curve= 0 ,0
Exp/Cntr=0.3,0.1

Type RM Length L Ch R = 1 ,4416.8  ,38,38.3,38
XS GIS Cut Line= 4
     1864987.274      560182.748     1865052.379      560106.793
     1865109.887       560059.05     1865220.564      559983.095
#Sta/Elev= 26
       0  669.97    36.4  669.29    45.5  669.02    63.7  668.19     100  666.69
   109.4  666.47   137.4  666.58   146.8  666.89   156.1   667.3   174.8  667.89
   184.4  667.51     194  664.91   203.6   660.7     207  659.88   213.1   658.4
     222  659.52   222.7  659.61   232.3  663.85   241.9   666.2   251.5  666.49
   261.1  667.88   270.7  671.13   280.2  674.76   289.8  677.55   299.4  679.64
     309  682.05
#Mann= 3 , 0 , 0
       0     .06       0     207    .045       0     222     .06       0
Bank Sta=207,222
XS Rating Curve= 0 ,0
Exp/Cntr=0.3,0.1

Type RM Length L Ch R = 1 ,4378.4  ,153,149.5,145.2
XS GIS Cut Line= 4
     1865008.976       560213.13      1865074.08      560137.175
     1865131.589      560089.432     1865242.266      560013.477
#Sta/Elev= 27
       0  668.04    18.2  666.45    27.3   665.8    36.4  665.52    63.7  665.21
    90.9  665.07   109.4  664.32   118.7  663.66   128.1  663.44   137.4  663.08
   146.8  662.46   156.1  662.16   165.4  661.57   174.8  661.58   184.4  661.04
   197.7  658.92   203.6     658   213.1  657.63   222.7  659.18   232.3  662.96
   241.9  666.07   251.5  666.61   261.1  667.76   270.7  670.65   280.2  674.22
   289.8  677.06     309   680.4
#Mann= 3 , 0 , 0
       0     .06       0   197.7    .045       0   222.7     .06       0
Bank Sta=197.7,222.7
XS Rating Curve= 0 ,0
Exp/Cntr=0.3,0.1

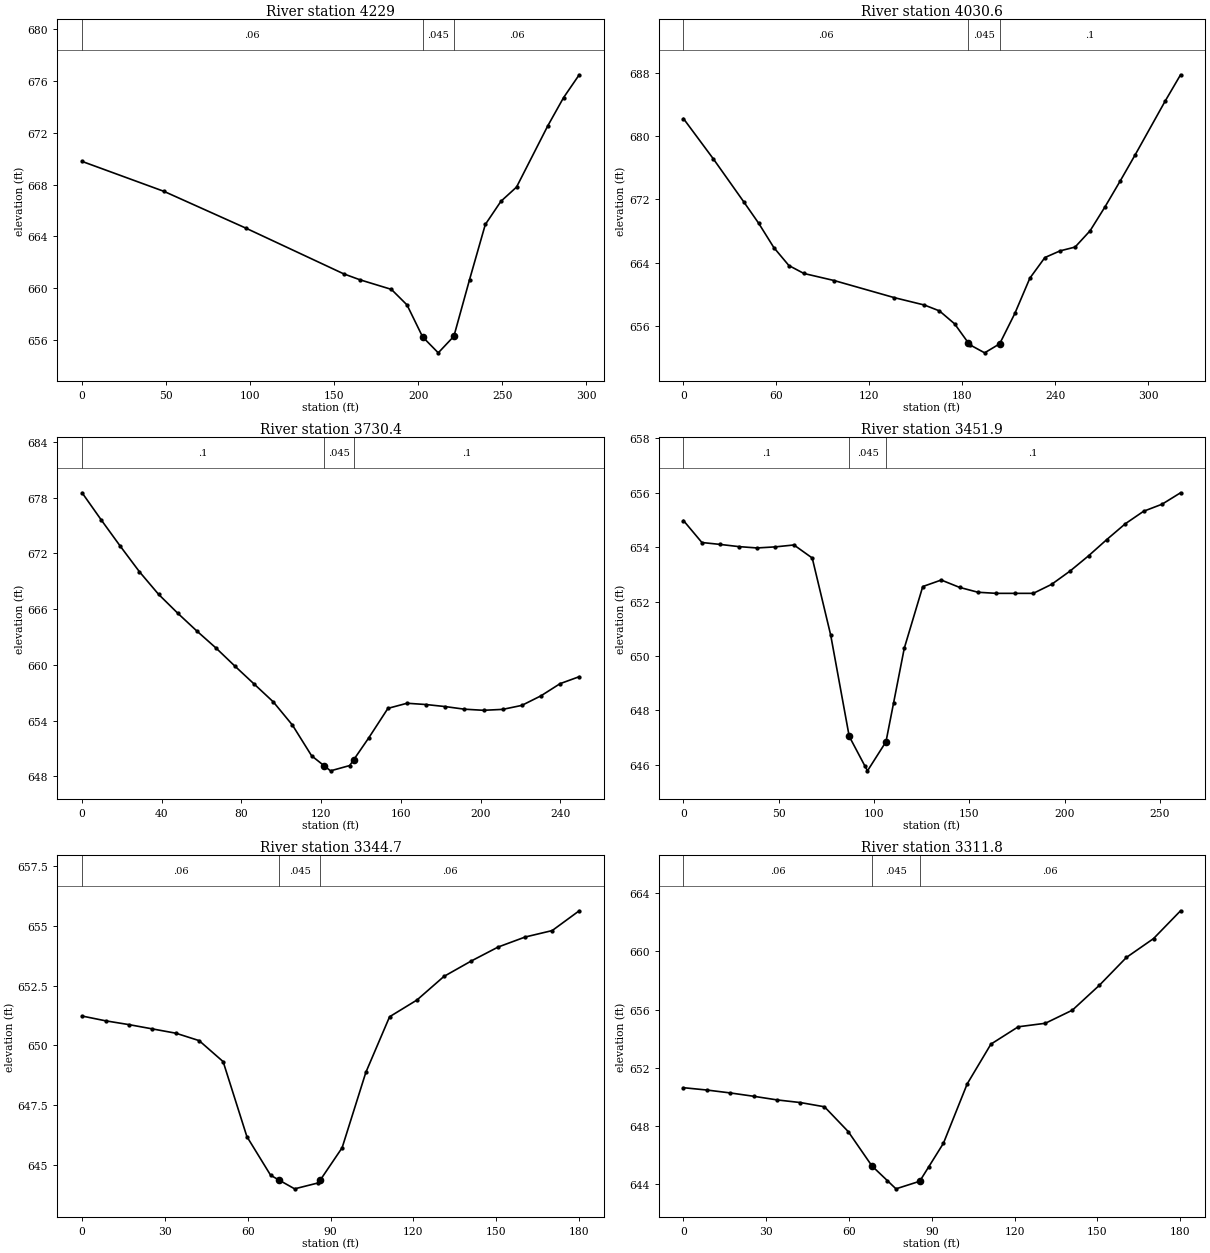
Type RM Length L Ch R = 1 ,4229    ,201.1,198.3,195.9
XS GIS Cut Line= 3
     1865081.675      560265.213      1865234.67      560202.279
     1865327.986      560111.133
#Sta/Elev= 17
       0  669.79    48.7  667.48    97.3  664.65   155.7  661.11   165.4  660.65
   184.1  659.91   193.4  658.71   202.7  656.24     212  655.01   221.3  656.29
   230.6  660.65     240  664.92   249.3  666.71   258.6  667.81   277.2  672.54
   286.6  674.72   295.9  676.48
#Mann= 3 , 0 , 0
       0     .06       0   202.7    .045       0   221.3     .06       0
Bank Sta=202.7,221.3
XS Rating Curve= 0 ,0
Exp/Cntr=0.3,0.1

Type RM Length L Ch R = 1 ,4030.6  ,302,300.2,298.3
XS GIS Cut Line= 2
     1865293.264      560449.675     1865495.087      560200.109
#Sta/Elev= 27
       0  682.21    19.4   677.1    38.9  671.72    48.6     669    58.4  665.93
    68.1  663.67    77.8  662.67    97.3  661.78   136.2  659.62   155.6  658.69
   165.3  657.95   175.1  656.32   183.9  653.93   184.8  653.69   194.5  652.66
   204.2   653.8     214  657.63   223.7  662.08   233.4  664.68   243.2  665.52
   252.9     666   262.6  668.06   272.3   671.1   282.1  674.36   291.8  677.67
   311.2  684.46     321  687.73
#Mann= 3 , 0 , 0
       0     .06       0   183.9    .045       0   204.2      .1       0
Bank Sta=183.9,204.2
XS Rating Curve= 0 ,0
Exp/Cntr=0.3,0.1

Type RM Length L Ch R = 1 ,3730.4  ,294.6,278.5,262.1
XS GIS Cut Line= 2
     1865546.085      560617.861     1865684.974      560410.612
#Sta/Elev= 29
       0  678.53     9.6  675.61    19.2  672.77    28.8  670.02    38.4  667.59
      48  665.56    57.6  663.64    67.2  661.81    76.8  659.84    86.4  657.92
      96     656   105.6   653.5   115.2   650.2   121.4  649.14   124.7  648.58
   134.3  649.15   136.4   649.8   143.9  652.14   153.5  655.31   163.1  655.86
   172.7  655.72   182.3   655.5   191.9  655.22   201.5   655.1   211.1   655.2
   220.7  655.63   230.3  656.66   239.9  657.97   249.5  658.72
#Mann= 3 , 0 , 0
       0      .1       0   121.4    .045       0   136.4      .1       0
Bank Sta=121.4,136.4
XS Rating Curve= 0 ,0
Exp/Cntr=0.3,0.1

Type RM Length L Ch R = 1 ,3451.9  ,97.8,107.2,116.7
XS GIS Cut Line= 2
       1865857.5      560716.602     1865829.288       560457.27
#Sta/Elev= 30
       0  654.98     9.7  654.17    19.3   654.1      29  654.02    38.6  653.97
    48.3  654.01      58  654.08    67.6   653.6    77.3  650.76      87  647.04
    95.3  645.94    96.6  645.77   106.3  646.84   110.3  648.27   115.9  650.28
   125.6  652.55   135.3  652.79   144.9  652.52   154.6  652.34   164.2   652.3
   173.9   652.3   183.6   652.3   193.2  652.63   202.9  653.12   212.6  653.68
   222.2  654.28   231.9  654.86   241.5  655.32   251.2  655.58   260.9     656
#Mann= 3 , 0 , 0
       0      .1       0      87    .045       0   106.3      .1       0
Bank Sta=87,106.3
XS Rating Curve= 0 ,0
Exp/Cntr=0.3,0.1

Type RM Length L Ch R = 1 ,3344.7  ,33.3,32.9,32.6
XS GIS Cut Line= 4
     1865937.795      560669.944      1865941.05      560627.626
     1865960.582      560561.437     1865996.389      560502.843
#Sta/Elev= 23
       0  651.23     8.5  651.03      17  650.87    25.5  650.69      34  650.51
    42.4   650.2    51.1  649.32    59.7  646.18    68.3  644.56    71.3  644.36
      77  643.99    85.6  644.24    86.3  644.36    94.2  645.71   102.8  648.87
   111.4   651.2   121.3   651.9   131.1  652.89   140.9  653.53   150.7  654.12
   160.5  654.54   170.3  654.81   180.1  655.64
#Mann= 3 , 0 , 0
       0     .06       0    71.3    .045       0    86.3     .06       0
Bank Sta=71.3,86.3
XS Rating Curve= 0 ,0
Exp/Cntr=0.3,0.1

Type RM Length L Ch R = 1 ,3311.8  ,51,54.6,58.2
XS GIS Cut Line= 4
     1865969.262      560672.114     1865972.517      560629.796
     1865992.049      560563.607     1866027.856      560505.013
#Sta/Elev= 23
       0  650.64     8.5  650.48      17  650.28    25.5  650.05      34   649.8
    42.4  649.62    51.1  649.33    59.7  647.63    68.3  645.27    73.9  644.26
      77   643.7    85.6  644.22    88.9  645.22    94.2  646.83   102.8   650.9
   111.4  653.63   121.3  654.82   131.1  655.06   140.9  655.96   150.7  657.67
   160.5  659.58   170.3  660.87   180.1  662.78
#Mann= 3 , 0 , 0
       0     .06       0    68.3    .045       0    85.6     .06       0
Bank Sta=68.3,85.6
XS Rating Curve= 0 ,0
Exp/Cntr=0.3,0.1

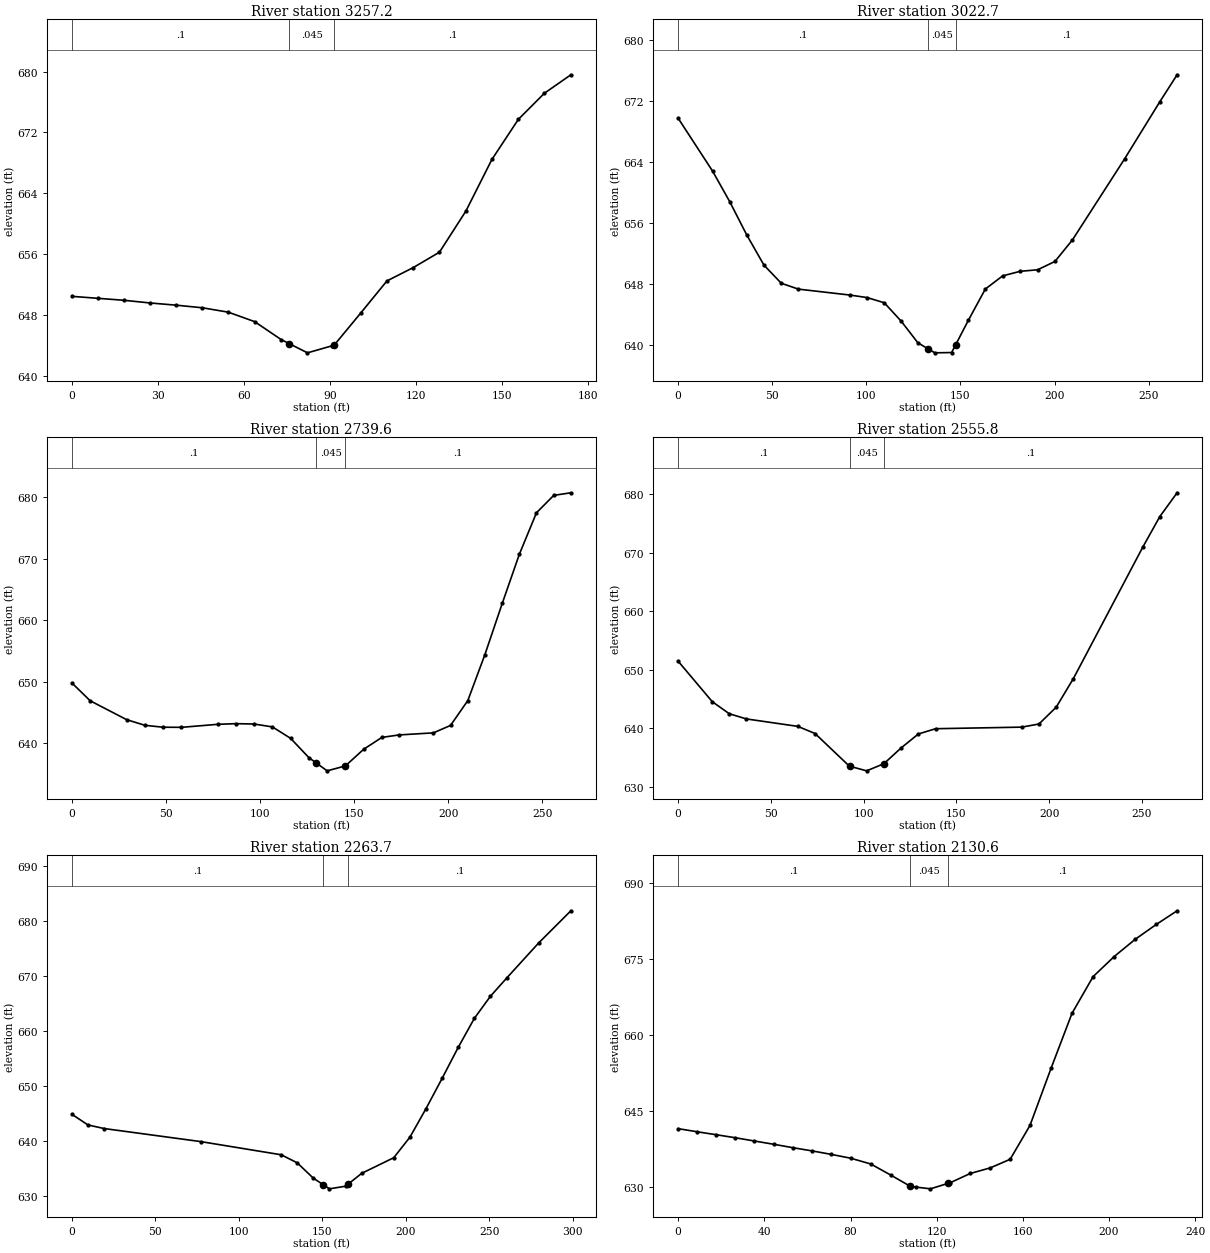
Type RM Length L Ch R = 1 ,3257.2  ,230.6,234.5,238.5
XS GIS Cut Line= 4
     1865980.113       560681.88     1866019.175      560643.902
     1866043.047      560593.989     1866073.429      560537.565
#Sta/Elev= 22
       0  650.44     9.1  650.18    18.2  649.92    27.2  649.57    36.3  649.28
    45.4  648.94    54.5  648.36    63.7  647.11    72.9  644.76    75.8  644.21
    82.1  643.01    90.8  643.95    91.4  644.02   100.6  648.22   109.8  652.47
     119  654.23   128.1  656.25   137.3  661.65   146.4  668.46   155.6  673.72
   164.7  677.16   173.9  679.58
#Mann= 3 , 0 , 0
       0      .1       0    75.8    .045       0    91.4      .1       0
Bank Sta=75.8,91.4
XS Rating Curve= 0 ,0
Exp/Cntr=0.3,0.1

Type RM Length L Ch R = 1 ,3022.7  ,277.1,283.1,288.8
XS GIS Cut Line= 4
     1866128.767      560886.958     1866189.531      560795.812
     1866220.998      560752.409     1866266.571      560661.263
#Sta/Elev= 26
       0  669.74    18.3  662.79    27.4  658.78    36.5  654.38    45.6  650.44
    54.8  648.06    63.9  647.29    91.3  646.51   100.4  646.18   109.5   645.5
   118.5  643.08   127.4  640.23   132.5  639.49   136.4  638.92   145.3  638.96
   147.5  640.01   154.2   643.2   163.2   647.3   172.4  649.03   181.7  649.63
     191  649.83   200.2  650.93   209.5  653.76   237.3  664.44   255.8  671.86
   265.1  675.45
#Mann= 3 , 0 , 0
       0      .1       0   132.5    .045       0   147.5      .1       0
Bank Sta=132.5,147.5
XS Rating Curve= 0 ,0
Exp/Cntr=0.3,0.1

Type RM Length L Ch R = 1 ,2739.6  ,181.2,183.8,186.4
XS GIS Cut Line= 3
      1866324.08      561010.656     1866449.948      560904.319
     1866504.201      560819.684
#Sta/Elev= 27
       0  649.76     9.7  646.86    29.1  643.78    38.8  642.86    48.5  642.55
    58.2  642.53    77.5  643.02    87.2  643.13    96.9  643.07   106.6   642.6
   116.3  640.73     126  637.59   129.9  636.73   135.7  635.44   145.4  636.24
   155.1  638.95   164.8  640.89   173.9  641.29   192.2  641.63   201.3  642.84
   210.5  646.89   219.6   654.4   228.8  662.72   237.9  670.74     247   677.5
   256.2  680.34   265.3  680.76
#Mann= 3 , 0 , 0
       0      .1       0   129.9    .045       0   145.4      .1       0
Bank Sta=129.9,145.4
XS Rating Curve= 0 ,0
Exp/Cntr=0.3,0.1

Type RM Length L Ch R = 1 ,2555.8  ,290.6,292.1,293.6
XS GIS Cut Line= 4
     1866449.948      561145.204     1866494.436      561098.546
     1866610.538      561021.506     1866656.111      560974.848
#Sta/Elev= 20
       0  651.48    18.4  644.57    27.6  642.51    36.8  641.63    64.5  640.36
    73.8  639.14    92.3  633.57    92.7  633.54   101.6  632.77   110.9  633.98
   120.2  636.68   129.5  639.06   138.8  639.96   185.2  640.23   194.5  640.76
   203.8  643.63   213.1  648.53   250.4   670.9   259.7  676.18     269  680.23
#Mann= 3 , 0 , 0
       0      .1       0    92.7    .045       0   110.9      .1       0
Bank Sta=92.7,110.9
XS Rating Curve= 0 ,0
Exp/Cntr=0.3,0.1

Type RM Length L Ch R = 1 ,2263.7  ,133.5,133,132.6
XS GIS Cut Line= 2
     1866583.412      561370.899     1866842.743      561222.244
#Sta/Elev= 22
       0  644.87     9.6  642.93    19.3  642.28    77.1  639.91   125.4  637.51
     135  636.04   144.6  633.26   150.4   632.1   154.3  631.32   163.9   631.8
   165.4  632.16   173.6  634.14   192.8  636.98   202.5  640.72   212.1  645.89
   221.8  651.42   231.4  657.03   241.1  662.32   250.7  666.32   260.4  669.62
   279.6  676.01   298.9  681.86
#Mann= 3 , 0 , 0
       0      .1       0   150.4    .045       0   165.4      .1       0
Bank Sta=150.4,165.4
XS Rating Curve= 0 ,0
Exp/Cntr=0.3,0.1

Type RM Length L Ch R = 1 ,2130.6  ,131.6,131.5,130.6
XS GIS Cut Line= 4
     1866687.578      561462.045     1866750.512      561429.493
     1866829.722      561381.749     1866877.465      561332.921
#Sta/Elev= 28
       0  641.56     8.9  640.94    17.7  640.36    26.6  639.76    35.4  639.12
    44.3  638.48    53.1  637.81      62  637.18    70.8   636.5    80.1  635.72
    89.4  634.58    98.6  632.41   107.8  630.16   110.4  630.02   117.1  629.67
   125.4  630.77   126.4   630.9   135.6  632.71   144.8   633.8   154.1  635.51
   163.3  642.19   173.1   653.5   182.8  664.34   192.6   671.6   202.4  675.57
   212.1  678.96   221.9   681.9   231.6  684.61
#Mann= 3 , 0 , 0
       0      .1       0   107.8    .045       0   125.4      .1       0
Bank Sta=107.8,125.4
XS Rating Curve= 0 ,0
Exp/Cntr=0.3,0.1