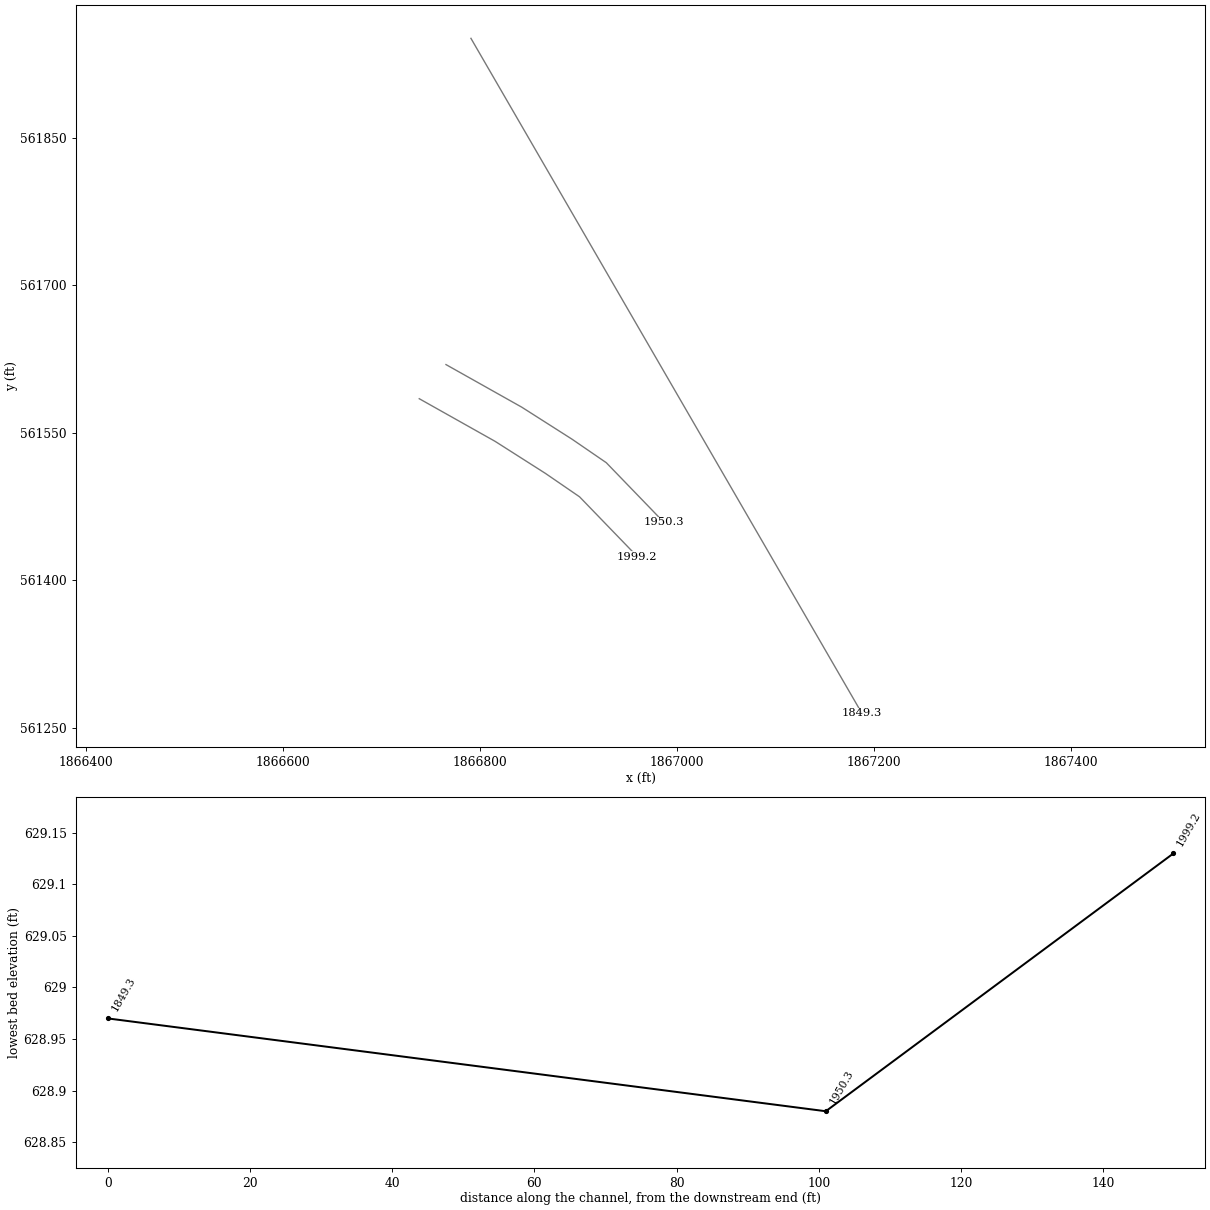
HEC-RAS study GABESCR.prj: GABESCR

--- GABESCR.g01 (geometry) --- (continued)

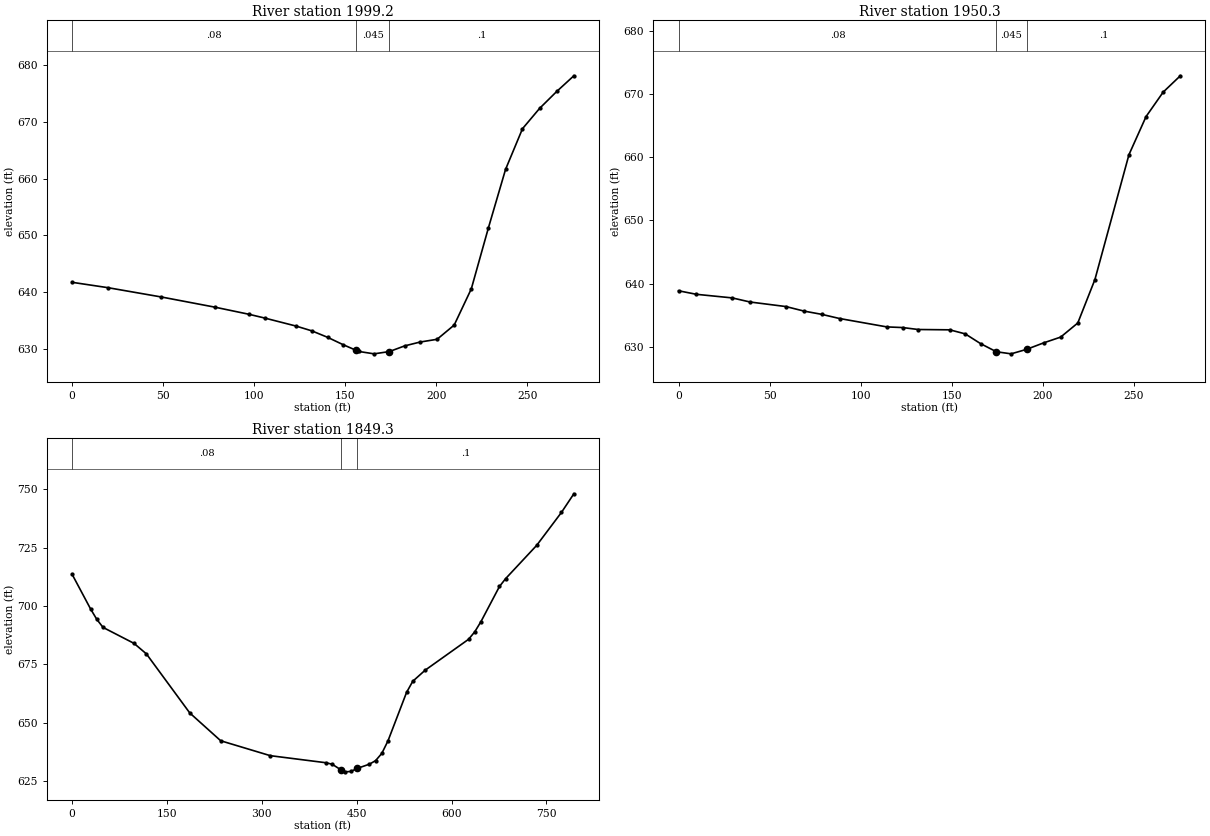
Type RM Length L Ch R = 1 ,1999.2  ,49,48.9,45.5
XS GIS Cut Line= 5
     1866738.576      561584.657     1866815.616      561541.255
     1866866.615      561508.703     1866901.337      561484.831
     1866959.931      561424.067
#Sta/Elev= 25
       0  641.73    19.6  640.79    49.1  639.14    78.6  637.34    97.1   636.1
   105.7  635.44     123  634.02   131.6  633.18   140.3  632.04   148.9  630.73
   155.9  629.76   157.4  629.55   165.8  629.13   174.2  629.53   182.6  630.53
   191.1  631.21   200.4  631.69   209.8   634.2   219.2  640.58   228.6  651.34
     238  661.62   247.3  668.79   256.7  672.37   266.1  675.35   275.5  678.11
#Mann= 3 , 0 , 0
       0     .08       0   155.9    .045       0   174.2      .1       0
Bank Sta=155.9,174.2
XS Rating Curve= 0 ,0
Exp/Cntr=0.3,0.1

Type RM Length L Ch R = 1 ,1950.3  ,112.1,101,93.8
XS GIS Cut Line= 5
     1866765.703       561619.38     1866842.743      561575.977
     1866893.741      561543.425     1866928.464      561519.553
     1866987.057      561458.789
#Sta/Elev= 25
       0  638.86     9.8   638.3    29.5  637.73    39.3  637.08      59  636.36
    68.8  635.65    78.6  635.13    88.4  634.47   114.4  633.14     123  633.04
   131.6  632.73   148.9  632.68   157.4  632.04   165.8   630.5   174.5  629.21
   182.6  628.88   191.1  629.59   200.4  630.61   209.8  631.53   219.2  633.76
   228.6  640.63   247.3   660.4   256.7  666.43   266.1   670.3   275.5  672.88
#Mann= 3 , 0 , 0
       0     .08       0   174.5    .045       0   191.1      .1       0
Bank Sta=174.5,191.1
XS Rating Curve= 0 ,0
Exp/Cntr=0.3,0.1

Type RM Length L Ch R = 1 ,1849.3  ,1891.2,1849.3,1807.1
XS GIS Cut Line= 2
      1866791.04      561951.298     1867188.024      561264.516
#Sta/Elev= 30
       0  713.56    29.4  698.63    39.2   694.2      49  690.79    97.9  683.97
   117.5  679.47   186.1  654.17     235  642.27   313.4  635.89   401.5  632.86
   411.3  632.21   425.9  629.68   430.9  628.97   440.7  629.12   450.5  630.41
   470.1  632.25   479.9  633.78   489.7  636.87   499.5  642.26   528.8  662.96
   538.6  667.73   558.2  672.48   626.8   685.7   636.6   688.9   646.4  693.26
   675.7  708.32   685.5   711.7   734.5  725.91   773.7  740.03   793.3     748
#Mann= 3 , 0 , 0
       0     .08       0   425.9    .045       0   450.5      .1       0
Bank Sta=425.9,450.5
XS Rating Curve= 0 ,0
Exp/Cntr=0.3,0.1

Chan Stop Cuts=-1
Use User Specified Reach Order=0
Composite Channel Slope=5